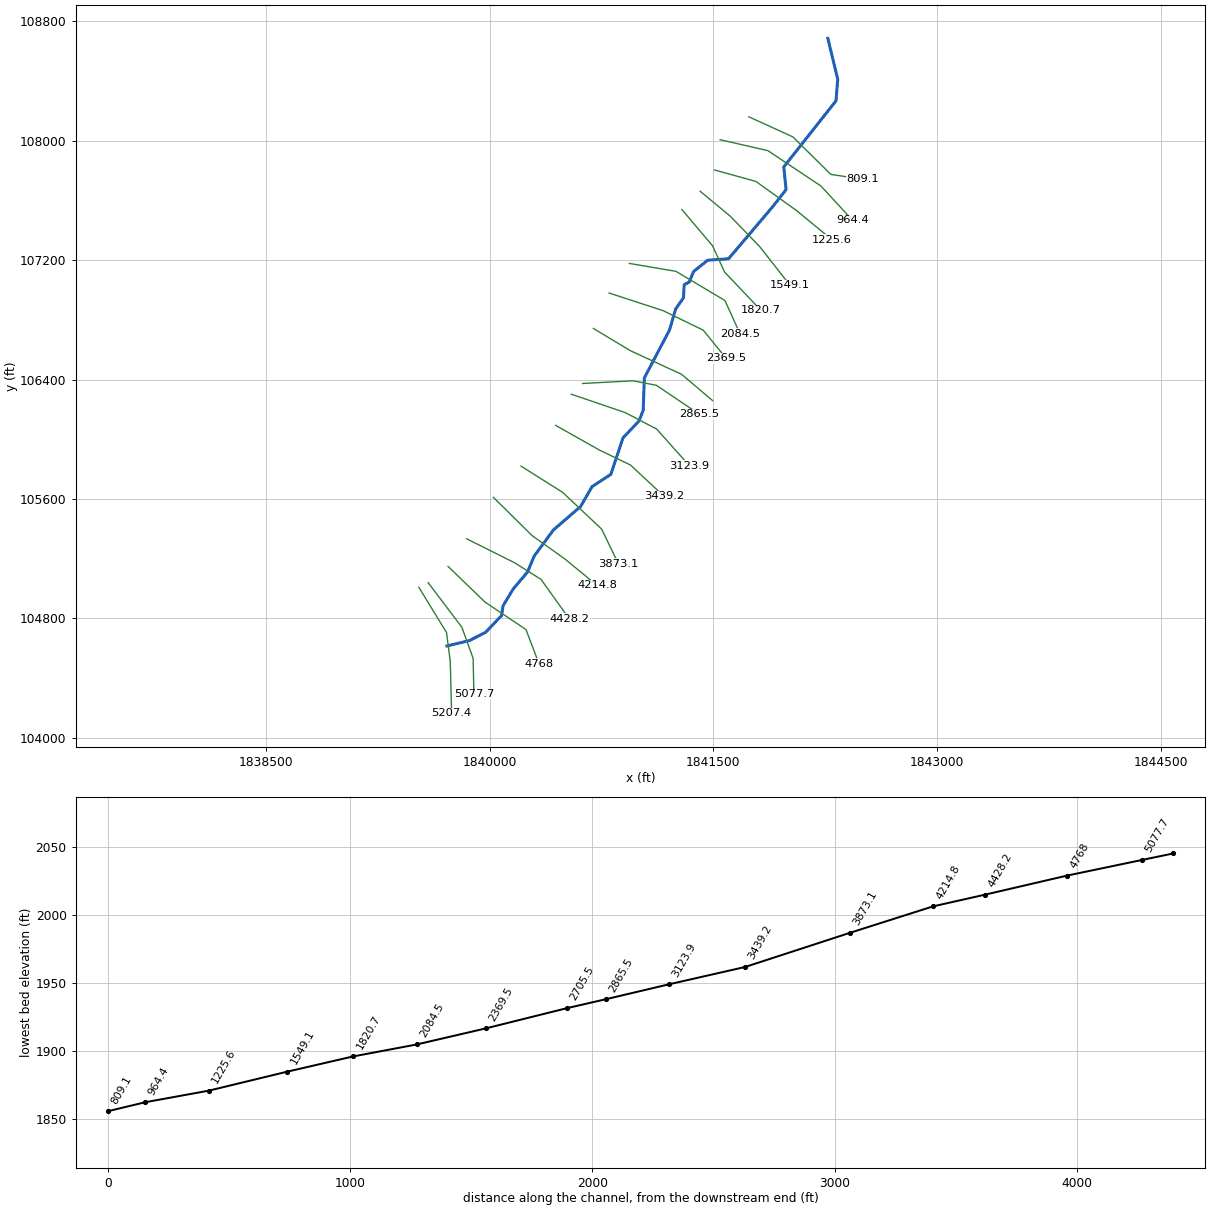
--- Ballard Harmon Branch.prj (project) ---

Proj Title=Ballard Harmon Branch
Current Plan=p01
Default Exp/Contr=0,0
English Units
Geom File=g01
Flow File=f01
Plan File=p01
BEGIN DESCRIPTION:
END DESCRIPTION:
DSS Export Rating Curves= 0
DSS Export Rating Curve Sorted= 0
DSS Export Volume Flow Curves= 0
DXF OffsetX= 0
DXF OffsetY= 0
DXF ScaleX= 0
DXF ScaleY= 0

--- Ballard Harmon Branch.p01 (plan) ---

Plan Title=Floodplain
Program Version=4.00
Geom File=g01
Flow File=f01
K Sum by GR=0
Std Step Tol=0.01
Critical Tol=0.01
Num of Std Step Trials=20
Max Error Tol=0.3
Flow Tol Ratio=0.001
Split Flow NTrial=30
Split Flow Tol=0.02
Split Flow Ratio=0.02
Log Output Level=0
Friction Slope Method=1
Unsteady Friction Slope Method=2
Unsteady Bridges Friction Slope Method=1
Global Log Level=0
CheckData=False
Run HTab=0
Run UNet=0
Run PostProcess=0
UNET Theta=0
UNET Theta Warmup=0
UNET ZTol=0
UNET ZSATol=0
UNET MxIter=0
UNET MaxInSteps=0
UNET DtIC=0
UNET DtMin=0
UNET MaxCRTS=0
UNET WFStab=0
UNET SFStab=0
UNET WFX=0
UNET SFX=0
UNET DSS MLevel=0
UNET DZMax Abort=0
UNET Convert EG Bridges=0
UNET Use Existing IB Tables=0
UNET Froude Limit=0
UNET Froude Power=0
Write IC File=0
Echo Input=False
Echo Output=False
Write Detailed=0

--- Ballard Harmon Branch.f01 (steady flow) ---

Flow Title=NFF Regression Equation
Program Version=4.00
Number of Profiles=1
Profile Names=P100yr
River Rch & RM=Ballard Harmo...,Main      ,5207.4
558.8006
River Rch & RM=Ballard Harmo...,Main      ,5077.7
559.4002
River Rch & RM=Ballard Harmo...,Main      ,4768
647.0856
River Rch & RM=Ballard Harmo...,Main      ,3873.1
661.7056
River Rch & RM=Ballard Harmo...,Main      ,2369.5
726.8108
Boundary for River Rch & Prof#=Ballard Harmo...,Main      ,1
Up Type=0
Dn Type=3
Dn Slope=0.039814

--- Ballard Harmon Branch.g01 (geometry) ---

Geom Title=USGS 10m DEM
Program Version=4.00

River Reach=Ballard Harmo...,Main
Reach XY= 30
     1839714.783      104614.807     1839866.247      104651.049
     1839974.939      104706.764      1840080.89      104818.653
     1840090.738       104883.88     1840159.118      104997.433
     1840254.431      105109.562     1840299.343      105217.293
     1840428.429      105392.251      1840610.97      105549.899
      1840686.72      105682.006     1840813.143      105764.929
     1840894.249      106008.779     1841001.571      106122.494
     1841029.885       106193.28     1841037.649       106411.12
     1841206.166      106731.714     1841247.725      106873.743
     1841299.787      106947.726      1841304.81      107035.867
     1841339.062      107053.678     1841367.377      107124.008
     1841461.911      107199.817     1841602.241      107209.999
     1841899.873      107561.057     1841987.653      107673.508
      1841972.03      107825.022     1842322.309      108268.465
     1842333.726      108413.234     1842267.415      108687.058

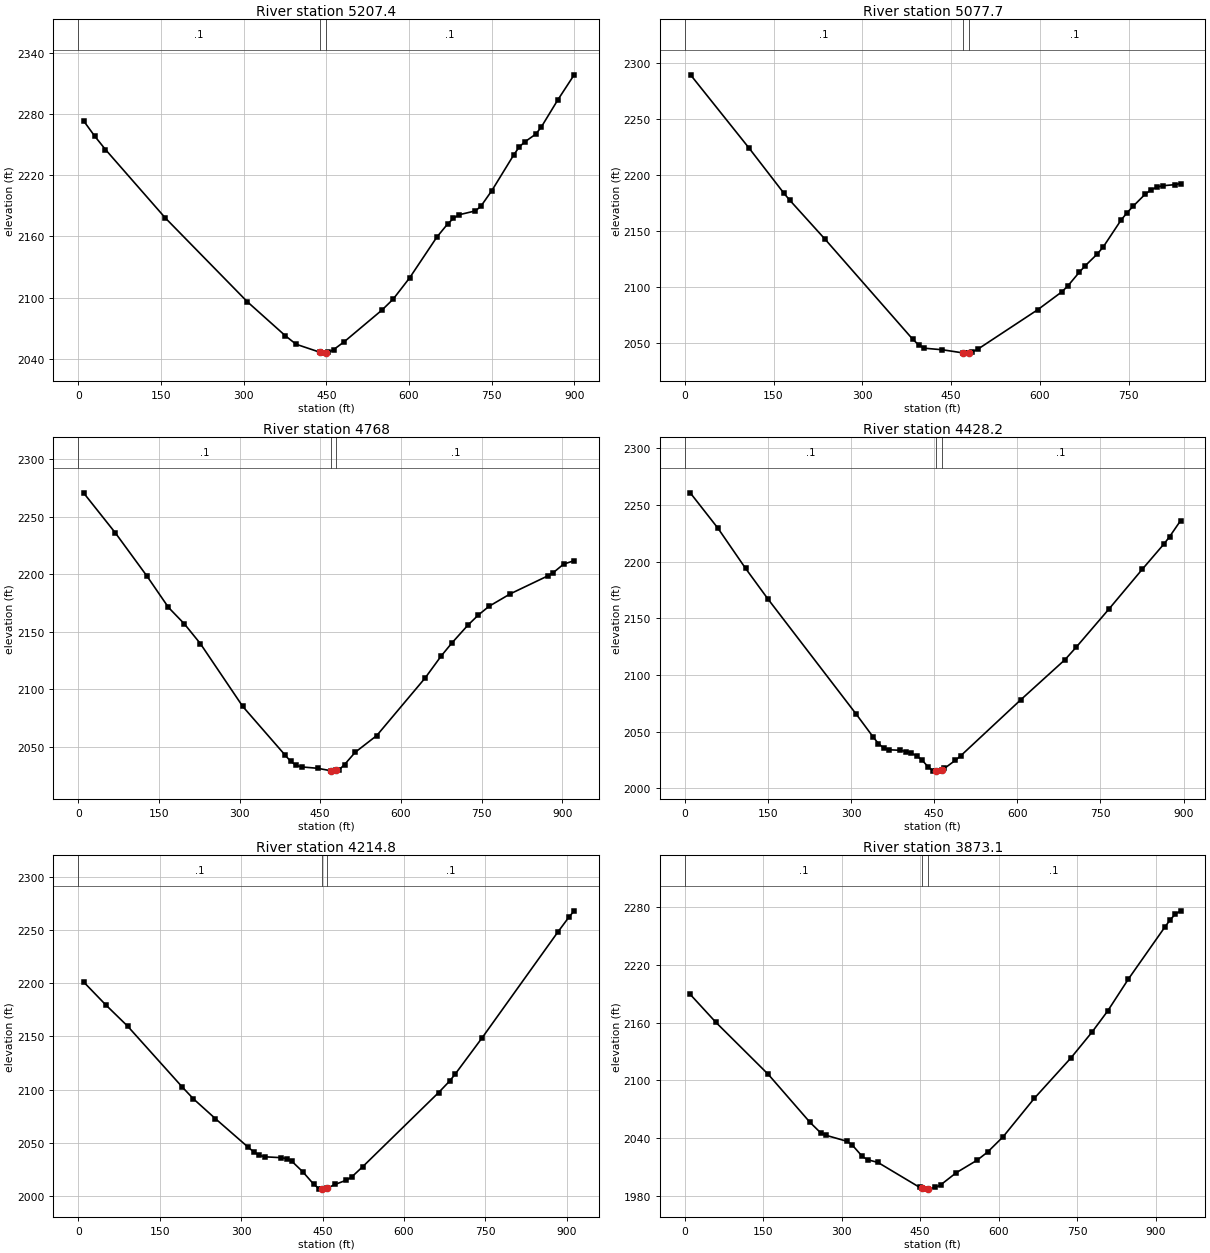
Type RM Length L Ch R = 1 ,5207.4  ,125.3,129.7,134
XS GIS Cut Line= 4
     1839526.028      105008.531      1839711.87      104704.654
     1839736.984      104511.278     1839745.976      104162.863
#Sta/Elev= 30
     9.9  2273.4    29.7 2258.61    49.5 2245.25   158.3 2177.98   306.7 2095.96
   375.7 2062.56   395.2 2054.21     439 2046.26     444 2045.48     449 2045.84
   453.7 2046.18   463.5 2048.98     483 2056.83   551.2 2087.82   571.1  2098.3
     601 2119.17   650.8  2159.5   670.7  2172.6   680.7 2177.68   690.6 2181.25
   720.5 2185.08   730.4 2189.56   750.4 2205.01   790.2 2240.12   800.2  2247.9
   810.1 2252.79     830 2260.41     840 2267.31   869.9  2293.9   899.7 2318.63
#Mann= 3 , 0 , 0
       0      .1       0     439    .045       0     449      .1       0
Bank Sta=439,449
XS Rating Curve= 0 ,0
Exp/Cntr=0.3,0.1

Type RM Length L Ch R = 1 ,5077.7  ,297.2,309.7,322.3
XS GIS Cut Line= 4
     1839588.812      105038.668     1839814.836      104739.813
     1839890.178      104531.369     1839895.201      104290.277
#Sta/Elev= 30
     9.9 2289.54   108.5 2224.17   167.6 2183.62   177.5 2177.39   236.7 2142.73
   384.8 2053.27   394.9 2048.07   404.9 2045.05   435.1 2043.67   470.4 2040.83
   475.4 2040.66   480.4 2041.15   485.5 2041.64   495.6 2044.38   596.3 2079.52
   636.5 2095.31   646.6 2100.48   666.7 2113.19   676.7 2118.95   696.8 2129.33
   706.9 2135.67     737  2159.7   747.1 2166.22   757.1 2171.92   777.2 2182.56
   787.2 2186.58   797.3 2189.13   807.3 2190.35   827.4  2191.3   837.5 2192.32
#Mann= 3 , 0 , 0
       0      .1       0   470.4    .045       0   480.4      .1       0
Bank Sta=470.4,480.4
XS Rating Curve= 0 ,0
Exp/Cntr=0.3,0.1

Type RM Length L Ch R = 1 ,4768    ,338.5,339.8,341.1
XS GIS Cut Line= 4
     1839722.052      105147.974     1839970.542      104908.076
     1840244.282      104724.745     1840332.181      104493.698
#Sta/Elev= 30
     9.9 2270.61    69.1 2235.81   128.3 2198.04   167.8 2171.17   197.4 2156.87
     227 2139.84   305.9 2085.27   385.3 2042.71   395.3  2037.5   405.3 2034.14
   415.3  2032.8   445.2  2031.6   470.2 2029.44   475.2 2029.14   480.2 2029.75
   485.2 2030.36   495.2 2034.86   515.1 2045.53   555.1 2060.02   644.9 2109.87
   674.9 2129.05   694.6 2140.24   724.3 2155.67   744.1 2164.65   763.8 2172.14
   803.4 2182.98   872.6 2198.43   882.5 2201.08   902.3 2208.66   922.1 2211.77
#Mann= 3 , 0 , 0
       0      .1       0   470.2    .045       0   480.2      .1       0
Bank Sta=470.2,480.2
XS Rating Curve= 0 ,0
Exp/Cntr=0.3,0.1

Type RM Length L Ch R = 1 ,4428.2  ,214.5,213.3,212.2
XS GIS Cut Line= 4
     1839847.484      105332.499     1840168.941      105171.771
     1840344.738       105061.27     1840535.602      104795.064
#Sta/Elev= 30
      10 2260.67    59.9 2229.51   109.8 2194.02   149.7 2167.29   309.5  2065.3
   339.4 2045.58   349.4 2039.43   359.4 2035.25   369.3 2033.91   389.1 2033.43
   398.9 2032.38   408.8 2030.86   418.7 2028.56   428.6 2024.64   438.5 2019.12
   448.4 2015.26   453.3 2015.17   458.3 2015.07   463.3 2016.24   468.2 2017.39
   487.9 2024.47   497.8 2028.54   606.7 2078.24   686.2 2113.51     706  2124.3
   765.6 2158.28   825.1 2193.01   864.8 2215.67   874.7 2221.97   894.6 2236.15
#Mann= 3 , 0 , 0
       0      .1       0   453.3    .045       0   463.3      .1       0
Bank Sta=453.3,463.3
XS Rating Curve= 0 ,0
Exp/Cntr=0.3,0.1

Type RM Length L Ch R = 1 ,4214.8  ,344.4,341.7,339
XS GIS Cut Line= 4
     1840025.911      105610.951     1840284.464      105355.101
     1840504.426      105198.126     1840720.681       105021.03
#Sta/Elev= 30
    10.1 2201.07    50.5 2179.73    90.9 2159.67     192 2102.23   212.2 2091.32
   252.6 2072.75   313.2  2045.8   323.3 2041.45   333.4 2038.34   343.5 2036.87
   373.8 2036.05   383.8  2035.2   393.8 2032.54   413.8 2022.71   433.8 2011.06
   443.8 2006.87   448.8 2006.69   453.8  2006.5   458.8 2007.53   473.8 2011.04
   493.9 2014.91   503.9    2018   523.9  2027.5   663.9 2097.26   683.9 2107.89
   693.9 2114.25   743.8 2148.54   883.5 2248.07   903.5 2261.79   913.5 2267.97
#Mann= 3 , 0 , 0
       0      .1       0   448.8    .045       0   458.8      .1       0
Bank Sta=448.8,458.8
XS Rating Curve= 0 ,0
Exp/Cntr=0.3,0.1

Type RM Length L Ch R = 1 ,3873.1  ,427.8,433.9,440.1
XS GIS Cut Line= 4
     1840211.634      105819.707     1840490.398       105643.91
     1840751.581      105397.795     1840864.593      105164.237
#Sta/Elev= 30
      10  2189.6    59.9 2160.11   159.8 2106.22   239.7 2056.33   259.7 2045.69
   269.6 2043.07   309.6 2036.86   319.6  2033.3   339.5 2021.06   349.5 2017.65
   369.4 2014.82   449.2 1988.91   454.2 1988.01   459.2 1987.11   464.2 1987.12
   479.1 1988.84   489.1 1991.44     519 2004.11   558.8  2017.1   578.8 2025.49
   608.7 2041.52   668.5 2081.51   738.3 2123.34   778.3 2149.93   808.2 2171.79
   848.1 2205.19     918  2259.3   927.9 2266.63   937.9 2272.65   947.9 2275.99
#Mann= 3 , 0 , 0
       0      .1       0   454.2    .045       0   464.2      .1       0
Bank Sta=454.2,464.2
XS Rating Curve= 0 ,0
Exp/Cntr=0.3,0.1

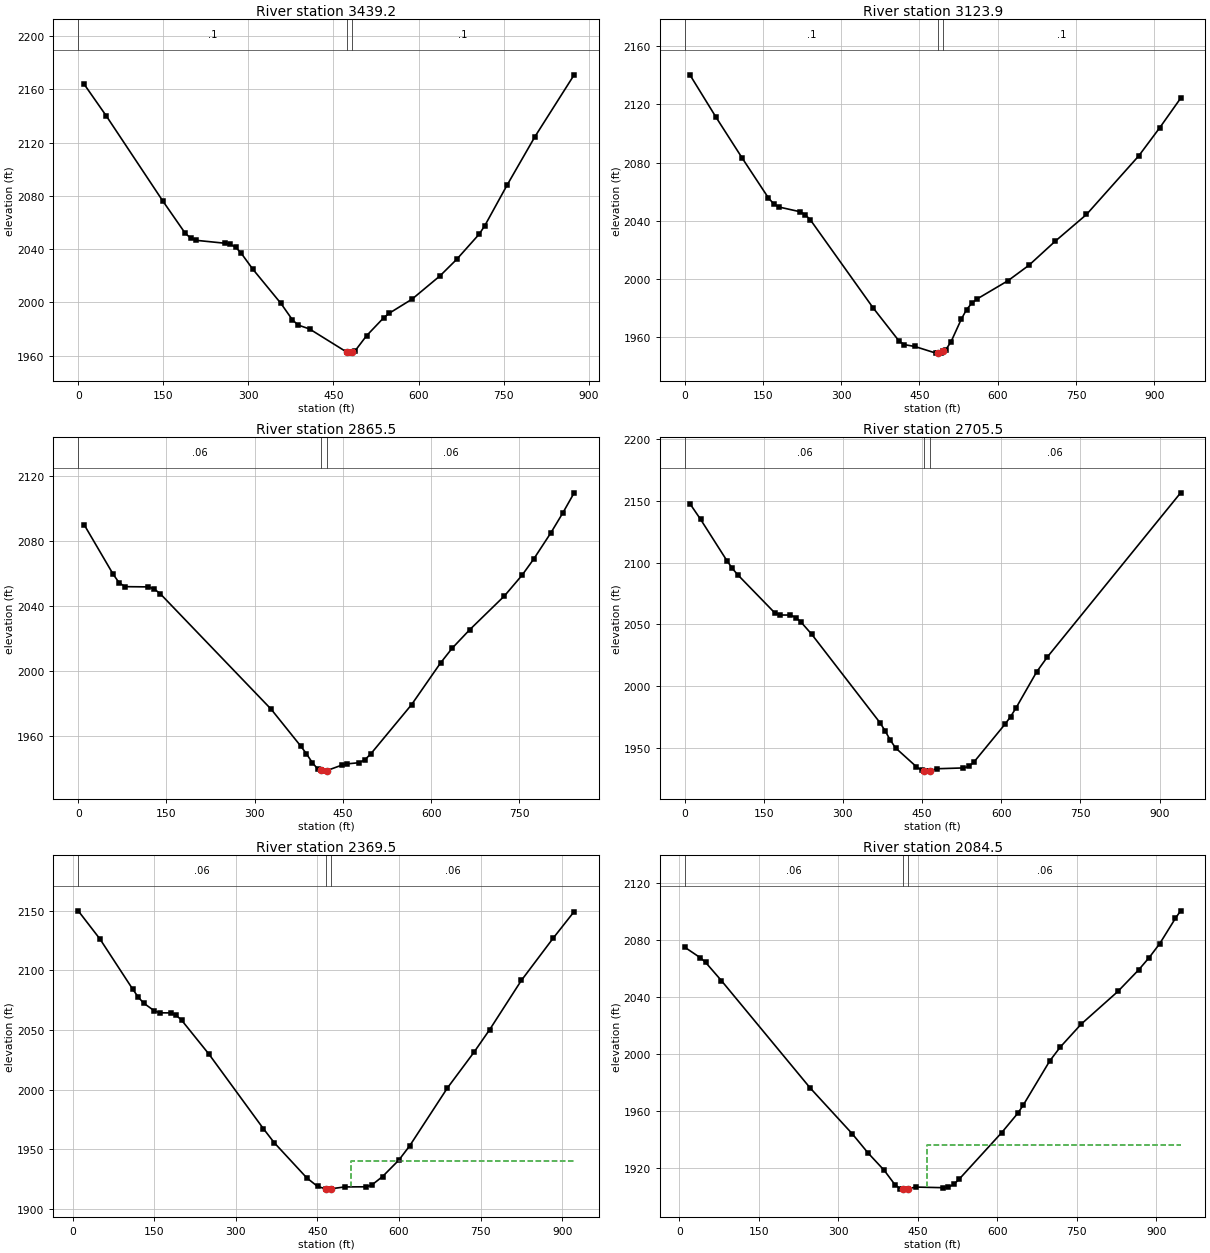
Type RM Length L Ch R = 1 ,3439.2  ,315.9,315.3,314.8
XS GIS Cut Line= 4
     1840442.681      106093.447     1840736.513      105927.696
     1840944.957      105827.241      1841168.47      105618.796
#Sta/Elev= 30
     9.9 2164.09    49.6 2139.89   148.8 2076.32   188.5 2051.97   198.4 2048.15
   208.4 2046.56     258 2044.42   267.9 2043.65   277.8 2041.35   287.7 2036.69
   307.6 2025.06   357.5 1999.17   377.6 1986.94   387.7 1982.98   407.8 1980.06
   473.2 1962.75   478.2 1961.91   483.2  1962.8   488.3  1963.7   508.4 1974.98
   538.6 1988.45   548.6 1991.92   588.5  2002.4   637.8 2019.87   667.3  2032.3
   706.8 2051.14   716.6 2057.37   756.1 2087.98   805.4 2124.48   874.4  2170.8
#Mann= 3 , 0 , 0
       0      .1       0   473.2    .045       0   483.2      .1       0
Bank Sta=473.2,483.2
XS Rating Curve= 0 ,0
Exp/Cntr=0.3,0.1

Type RM Length L Ch R = 1 ,3123.9  ,252.4,258.4,264.4
XS GIS Cut Line= 4
     1840547.941      106301.963     1840909.045      106178.959
        1841120.      106068.459     1841340.516      105821.907
#Sta/Elev= 30
      10 2140.29    60.2 2111.08   110.4    2083   160.6 2055.69   170.7 2051.61
   180.7 2049.49   220.9 2046.26   230.9 2044.26   240.9 2040.65   361.4 1980.07
   411.2 1957.26   421.2 1954.93     441 1953.69   480.7  1949.2   485.6 1949.16
   490.6 1949.12   495.6 1950.34   500.6 1951.56   510.5 1957.01   530.3 1972.58
   540.2 1979.05   550.2 1983.39   560.1 1986.27   619.6 1998.87   659.7 2009.47
   709.8  2025.9     770 2044.35   870.2 2084.63   910.3 2103.91   950.4  2124.2
#Mann= 3 , 0 , 0
       0      .1       0   485.6    .045       0   495.6      .1       0
Bank Sta=485.6,495.6
XS Rating Curve= 0 ,0
Exp/Cntr=0.3,0.1

Type RM Length L Ch R = 1 ,2865.5  ,164.8,160,155.1
XS GIS Cut Line= 4
     1840623.752      106373.842     1840961.281      106391.924
     1841117.991      106361.788      1841404.54      106168.788
#Sta/Elev= 30
     9.9 2090.32    59.6 2059.54    69.6  2054.4    79.5    2052   119.3 2051.85
   129.2 2050.56   139.2 2047.72   328.1 1976.37   377.9 1953.86   387.9    1949
   397.9 1943.49   407.8 1939.33   412.8 1938.79   417.8 1938.24   422.8  1938.6
   447.7 1941.88   457.7 1942.73   477.6 1943.44   487.6 1945.34   497.6 1948.97
   566.7 1979.23     616 2004.98   635.8 2014.07   665.4 2025.39   724.6  2046.3
   754.2  2058.9     774 2068.83   803.6 2085.25   823.3 2097.13   843.1 2109.86
#Mann= 3 , 0 , 0
       0     .06       0   412.8    .045       0   422.8     .06       0
Bank Sta=412.8,422.8
XS Rating Curve= 0 ,0
Exp/Cntr=0.3,0.1

Type RM Length L Ch R = 1 ,2705.5  ,336.4,336,335.6
XS GIS Cut Line= 4
     1840695.786       106742.93     1840944.957      106593.211
     1841286.795      106435.612     1841494.949      106259.198
#Sta/Elev= 30
      10 2147.42    30.1 2134.86    80.2 2101.38    90.2 2095.31   100.2 2090.26
   170.4 2059.52   180.4 2057.64   200.5 2057.61   210.5 2055.63   220.5 2051.92
   240.6 2042.19   369.9 1970.91   379.8 1964.28   389.7 1956.71   399.7 1950.43
   439.3  1935.2   449.2 1932.27   454.1 1931.98   459.1 1931.69   464.1 1932.19
   478.9 1933.62   528.4 1934.27   538.3 1935.43   548.2 1938.98   607.7 1969.84
   617.6 1975.58   627.5 1982.28   667.1 2011.73   687.3 2023.72     940 2156.22
#Mann= 3 , 0 , 0
       0     .06       0   454.1    .045       0   464.1     .06       0
Bank Sta=454.1,464.1
XS Rating Curve= 0 ,0
Exp/Cntr=0.3,0.1

Type RM Length L Ch R = 1 ,2369.5  ,285.6,285,284.1
XS GIS Cut Line= 4
     1840801.809      106979.964     1841163.447      106861.929
     1841432.165      106731.337     1841585.359      106542.984
#Sta/Elev= 30
      10 2149.79    50.1 2126.11   110.1 2084.28   120.1 2077.72   130.1  2072.6
   150.2 2065.96   160.2 2064.39   180.2 2064.32   190.2 2062.33   200.2 2058.18
   250.3 2029.85   350.4 1967.45   370.4 1955.66   430.2 1926.23   450.1 1919.04
     465 1916.99     470 1916.76     475 1917.05   499.9  1918.6   539.8 1918.71
   549.7 1920.14   569.6 1927.27   599.5 1941.01   619.4 1952.91   688.9 2001.46
   737.5 2031.19   766.6 2050.28   824.9 2091.51   883.1  2126.7     922 2149.16
#Mann= 3 , 0 , 0
      10     .06       0     465    .045       0     475     .06       0
#XS Ineff= 2 , 0
                          511.66         1940.71
Permanent Ineff=
       F       F
Bank Sta=465,475
XS Rating Curve= 0 ,0
Exp/Cntr=0.3,0.1

Type RM Length L Ch R = 1 ,2084.5  ,276.3,263.8,251.3
XS GIS Cut Line= 4
     1840937.423      107178.363     1841248.834      107125.624
     1841577.825      106929.736     1841679.971      106705.009
#Sta/Elev= 30
     9.9 2074.66    39.5 2067.24    49.4 2063.99      79 2051.28   246.8 1975.84
   325.9 1943.82   356.1  1930.2   386.4 1918.11   406.5 1908.11   416.6 1905.22
   421.7 1905.08   426.7 1904.94   431.7 1905.34   446.8 1906.38   497.2 1905.95
   507.3 1906.37   517.4 1908.21   527.4 1911.76   608.1 1944.62   638.3 1958.12
   648.4 1963.71   698.7 1994.88   718.5 2004.58     758 2020.69   827.1 2043.58
   866.6 2058.82   886.3 2067.39   906.1  2077.1   935.7 2094.87   945.6 2100.17
#Mann= 3 , 0 , 0
     9.9     .06       0   421.7    .045       0   431.7     .06       0
#XS Ineff= 2 , 0
                          467.18         1935.97
Permanent Ineff=
       F       F
Bank Sta=421.7,431.7
XS Rating Curve= 0 ,0
Exp/Cntr=0.3,0.1

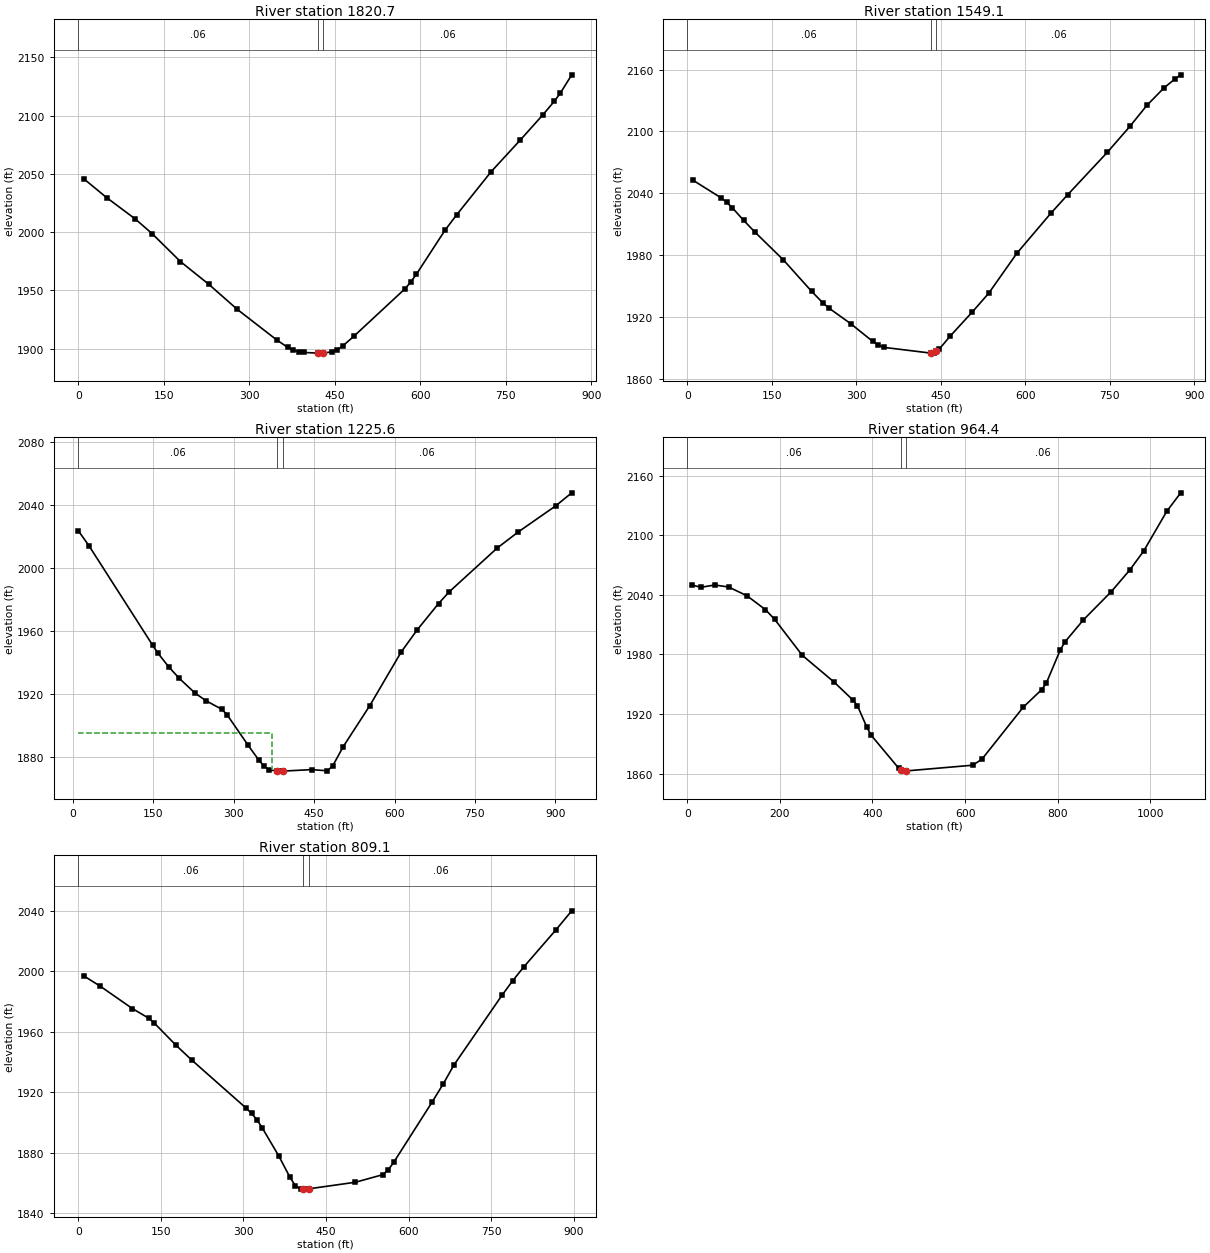
Type RM Length L Ch R = 1 ,1820.7  ,264.9,271.6,278.3
XS GIS Cut Line= 4
     1841289.016      107540.001     1841494.949      107296.398
     1841575.313      107120.601     1841818.917       106864.44
#Sta/Elev= 30
      10 2045.67    49.8 2029.64    99.7 2011.41   129.6 1998.71   179.4 1974.67
   229.3 1955.08   279.1 1933.62     348 1907.51   367.3 1901.11     377 1898.74
   386.6 1897.27   396.3 1896.65   420.3 1896.09   425.3 1896.08   430.3  1896.2
   444.6 1897.17   454.3  1899.1     464 1902.22   483.3 1910.42   572.9 1951.16
     583 1956.86   593.1 1963.68   643.6 2001.69   663.8 2014.77   724.4 2051.86
   774.9  2078.7   815.3 2100.78   835.5 2112.48   845.6 2119.18   865.8 2135.04
#Mann= 3 , 0 , 0
       0     .06       0   420.3    .045       0   430.3     .06       0
Bank Sta=420.3,430.3
XS Rating Curve= 0 ,0
Exp/Cntr=0.3,0.1

Type RM Length L Ch R = 1 ,1549.1  ,319.6,323.5,327.4
XS GIS Cut Line= 4
      1841411.76      107662.117      1841612.67      107495.738
     1841810.441      107291.689     1842014.491      107031.133
#Sta/Elev= 30
      10  2052.7    60.2  2035.5    70.2 2031.19    80.3 2025.75   100.3 2013.59
   120.4 2002.17   170.6 1975.35   220.7 1944.88   240.8  1933.6   250.8 1928.86
   290.3 1913.39   329.4  1896.2   339.2 1892.69     349 1890.48   432.2 1884.91
   437.2 1884.88   442.2 1886.75     447 1888.54   466.6 1901.31   505.8 1924.66
   535.2    1943   585.1 1981.75   645.3 2020.48   675.4  2038.6   745.6 2079.66
   785.7 2104.83   815.8 2125.21   845.9    2142   865.9 2150.98     876 2154.88
#Mann= 3 , 0 , 0
       0     .06       0   432.2    .045       0   442.2     .06       0
Bank Sta=432.2,442.2
XS Rating Curve= 0 ,0
Exp/Cntr=0.3,0.1

Type RM Length L Ch R = 1 ,1225.6  ,260.9,261.1,261.4
XS GIS Cut Line= 4
      1841508.17      107804.866     1841785.328      107728.041
     1842057.515      107532.959     1842295.391      107337.127
#Sta/Elev= 30
     9.9 2023.63    29.8  2014.1   148.8 1950.83   158.7 1945.78   178.5 1937.22
   198.4 1929.81   228.1 1920.41   247.9  1915.7   277.7  1910.2   287.6 1906.73
     327 1887.27   346.7 1877.98   356.6 1874.07   366.4 1871.73   381.1 1870.99
   386.1 1870.92   391.1 1870.93   445.2 1871.88   474.7 1871.13   484.6 1874.21
   504.3 1886.47   553.5 1912.31   612.6 1946.64   642.4 1960.66   682.1 1977.31
     702 1984.76   791.5 2012.55   831.2 2022.87   900.8 2039.37   930.6 2047.62
#Mann= 3 , 0 , 0
     9.9     .06       0   381.1    .045       0   391.1     .06       0
#XS Ineff= 2 , 0
          370.61 1895.15
Permanent Ineff=
       F       F
Bank Sta=381.1,391.1
XS Rating Curve= 0 ,0
Exp/Cntr=0.3,0.1

Type RM Length L Ch R = 1 ,964.4   ,159.2,155.4,151.5
XS GIS Cut Line= 4
     1841546.062      108007.445     1841865.551      107934.419
     1842221.552      107697.085     1842431.501      107468.879
#Sta/Elev= 30
     9.9 2049.91    29.8 2047.67    59.6 2049.93    89.4 2047.92   129.1 2039.08
   168.8 2025.14   188.7 2015.42   248.3 1979.18   317.8 1951.88   357.6 1934.16
   367.5 1928.41   387.4 1907.18   397.4 1898.49   457.1 1865.14     462 1863.81
     467 1862.45     472 1862.62   616.3  1868.4   636.2 1874.35   725.7 1926.91
   765.6 1944.62   775.6 1951.26   805.6 1984.59   815.6 1992.58   855.6 2014.87
   915.6 2043.19   955.6 2065.01   985.7 2084.17  1035.7 2124.28  1065.7 2142.79
#Mann= 3 , 0 , 0
       0     .06       0     462    .045       0     472     .06       0
Bank Sta=462,472
XS Rating Curve= 0 ,0
Exp/Cntr=0.3,0.1

Type RM Length L Ch R = 1 ,809.1   ,791.1,809.1,827.1
XS GIS Cut Line= 4
     1841738.239      108161.254     1842033.326      108026.267
     1842287.603      107775.129      1842499.15      107743.239
#Sta/Elev= 30
     9.8 1997.02    39.3  1990.3    98.3 1975.35   127.8 1968.99   137.7 1965.87
     177 1951.22   206.5  1941.1   304.8 1909.42   314.7 1905.89   324.5  1901.7
   334.4 1896.11   364.2 1877.67   384.1 1863.81     394  1858.1   403.9 1855.84
   408.8 1855.82   413.8  1855.8   418.8 1856.02   503.2 1860.36   552.8 1865.36
   562.8  1868.6   572.7 1873.56   642.2 1913.34     662 1925.11   681.9 1937.92
   769.4 1984.23   788.9  1993.9   808.3  2002.7   866.6 2027.22   895.8 2040.04
#Mann= 3 , 0 , 0
       0     .06       0   408.8    .045       0   418.8     .06       0
Bank Sta=408.8,418.8
XS Rating Curve= 0 ,0
Exp/Cntr=0.3,0.1

Chan Stop Cuts=-1
Use User Specified Reach Order=0